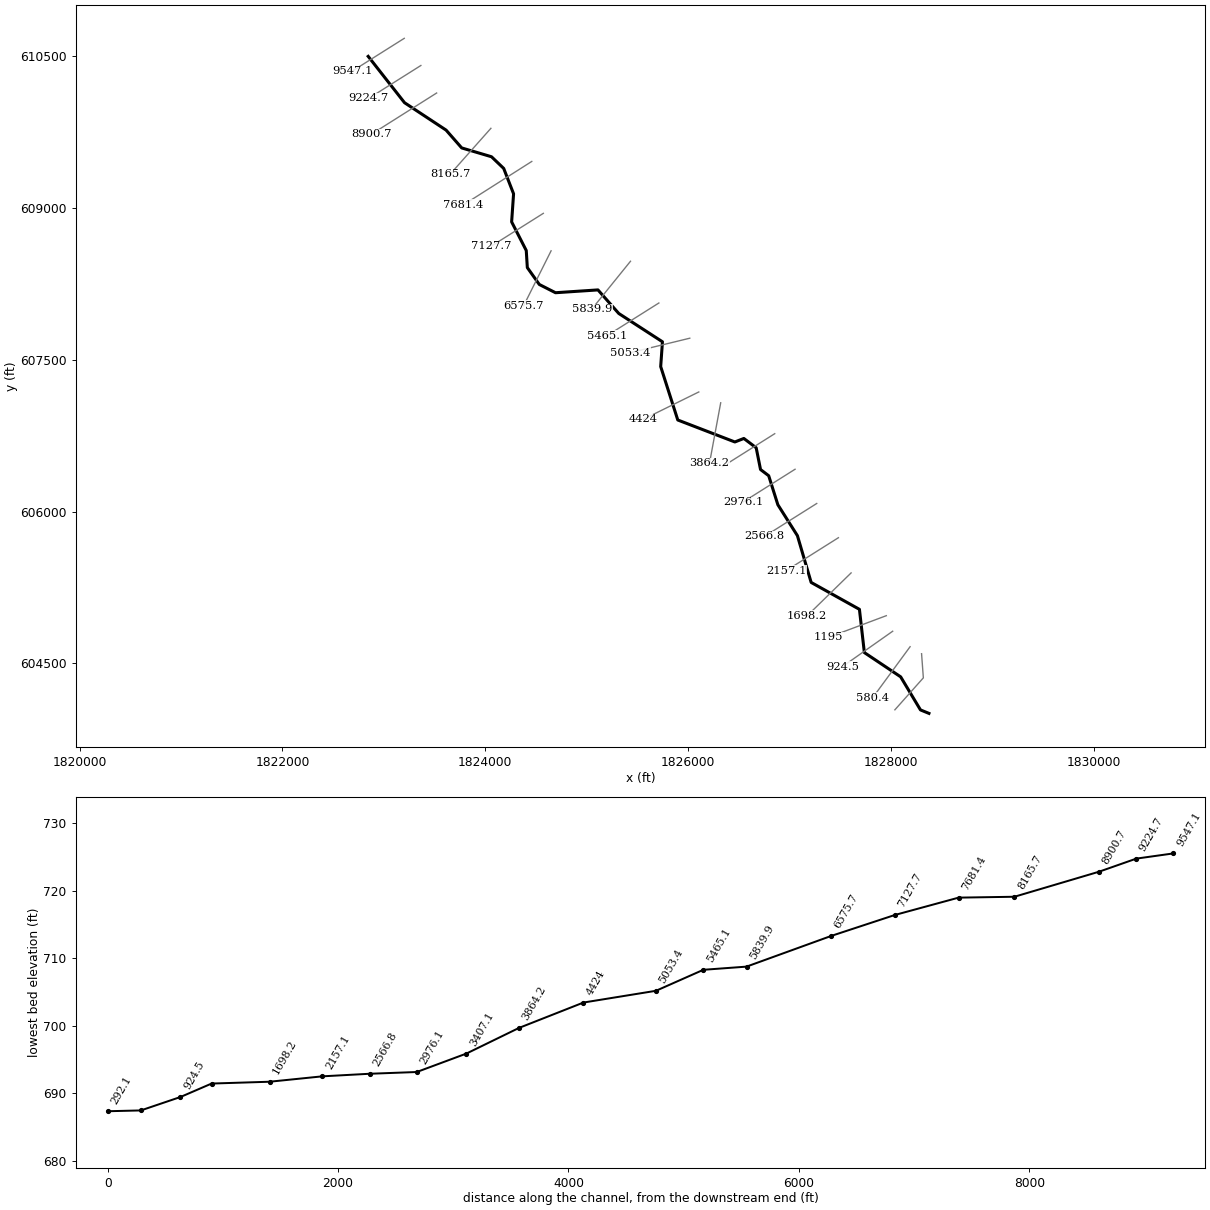
--- HigbyRun.prj (project) ---

Proj Title=HigbyRun
Current Plan=p01
Default Exp/Contr=0,0
English Units
Geom File=g01
Flow File=f01
Plan File=p01
BEGIN DESCRIPTION:
AMEC Environment & Infrastructure, 2013
Projection: NAD 1983 State Plane West Virginia South FIPS 4702 (US Feet)
Vertical Datum: NAVD 1988
END DESCRIPTION:
DSS Export Rating Curves= 0
DSS Export Rating Curve Sorted= 0
DSS Export Volume Flow Curves= 0
DXF OffsetX= 0
DXF OffsetY= 0
DXF ScaleX= 0
DXF ScaleY= 0

--- HigbyRun.p01 (plan) ---

Plan Title=Floodplain
Program Version=4.00
Geom File=g01
Flow File=f01
K Sum by GR=0
Std Step Tol=0.01
Critical Tol=0.01
Num of Std Step Trials=20
Max Error Tol=0.3
Flow Tol Ratio=0.001
Split Flow NTrial=30
Split Flow Tol=0.02
Split Flow Ratio=0.02
Log Output Level=0
Friction Slope Method=1
Unsteady Friction Slope Method=2
Unsteady Bridges Friction Slope Method=1
Global Log Level=0
CheckData=False
Run HTab=0
Run UNet=0
Run PostProcess=0
UNET Theta=0
UNET Theta Warmup=0
UNET ZTol=0
UNET ZSATol=0
UNET MxIter=0
UNET MaxInSteps=0
UNET DtIC=0
UNET DtMin=0
UNET MaxCRTS=0
UNET WFStab=0
UNET SFStab=0
UNET WFX=0
UNET SFX=0
UNET DSS MLevel=0
UNET DZMax Abort=0
UNET Convert EG Bridges=0
UNET Use Existing IB Tables=0
UNET Froude Limit=0
UNET Froude Power=0
Write IC File=0
Echo Input=False
Echo Output=False
Write Detailed=0

--- HigbyRun.f01 (steady flow) ---

Flow Title=NFF Regression Equation
Program Version=4.00
Number of Profiles=1
Profile Names=P100yr
River Rch & RM=HigbyRun,Main      ,9547.1
1245.471
River Rch & RM=HigbyRun,Main      ,8165.7
1318.223
River Rch & RM=HigbyRun,Main      ,6575.7
1415.503
River Rch & RM=HigbyRun,Main      ,580.4
1567.070
River Rch & RM=HigbyRun,Main      ,292.1
1567.070
Boundary for River Rch & Prof#=HigbyRun,Main      ,1
Up Type=0
Dn Type=3
Dn Slope=0.004545

--- HigbyRun.g01 (geometry) ---

Geom Title=USGS 3m DEM
Program Version=4.10

River Reach=HigbyRun        ,Main
Reach XY= 30
     1822845.807      610496.357      1823203.85      610038.776
     1823613.727      609767.876     1823767.606      609591.881
     1824061.471      609504.679     1824181.649      609389.309
     1824278.919      609138.629     1824259.832      608861.357
     1824403.994      608578.284     1824414.424      608409.825
      1824532.53      608243.109     1824692.311      608161.493
     1825110.853      608189.305     1825315.797      607956.599
     1825746.514      607677.016     1825729.161      607432.141
     1825897.651      606904.194     1826460.354      606687.139
     1826548.924      606721.878     1826670.497       606629.84
     1826713.325      606415.023     1826793.819      606353.712
     1826884.143      606067.162     1827076.934      605761.515
     1827212.423       605299.56     1827688.292      605033.873
     1827736.944      604606.648     1828094.717      604367.004
     1828290.198      604040.179     1828373.673      604006.083

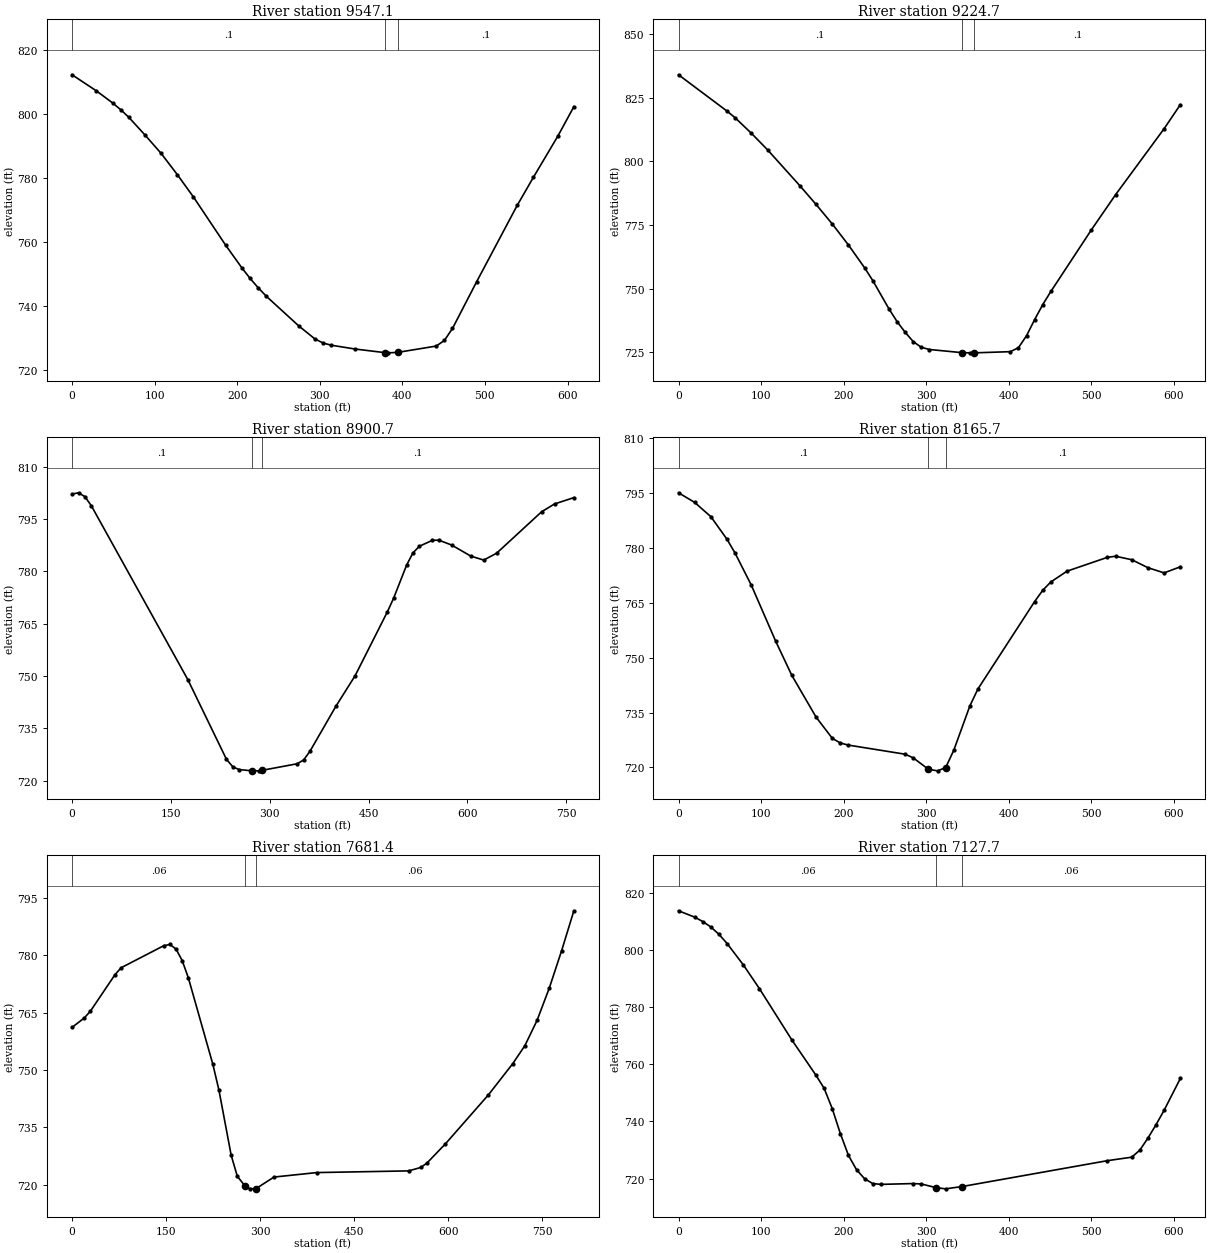
Type RM Length L Ch R = 1 ,9547.1  ,322,322,321.9
XS GIS Cut Line= 2
     1823201.215      610674.522     1822687.402      610350.009
#Sta/Elev= 30
       0  812.33    29.4  807.32      49  803.55    58.8  801.45    68.6  799.08
    88.2  793.56   107.8   787.8   127.4  781.17     147  774.17   186.2  759.04
   205.8  751.98   215.6  748.74   225.4  745.82   235.2  743.18   274.4  733.94
     294  729.86   303.9  728.58   313.7  727.89   343.1  726.68   379.3  725.55
   382.3   725.5   394.3  725.64   441.1  727.62   450.9  729.37   460.7  733.11
   490.1  747.77   539.1  771.55   558.7  780.32   588.1  793.08   607.7  802.36
#Mann= 3 , 0 , 0
       0      .1       0   379.3    .045       0   394.3      .1       0
Bank Sta=379.3,394.3
XS Rating Curve= 0 ,0
Exp/Cntr=0.3,0.1

Type RM Length L Ch R = 1 ,9224.7  ,323.8,323.7,323.5
XS GIS Cut Line= 2
     1823365.187      610406.214     1822851.373      610081.701
#Sta/Elev= 30
       0  833.99    58.8   819.7    68.6  817.08    88.2  811.01   107.8  804.51
     147  790.37   166.6  783.03   186.2  775.36   205.8   767.1   225.4  758.12
   235.2  753.15   254.8  742.03   264.6  737.03   274.4  732.83   284.2  729.16
     294  726.91   303.9  726.04   343.4   724.8   352.9  724.73   358.4  724.73
   401.9  725.19   411.7  726.77   421.5  731.48   431.3  737.82   441.1  743.69
   450.9  748.84   499.9  773.02   529.3  786.88   588.1  812.82   607.7  822.24
#Mann= 3 , 0 , 0
       0      .1       0   343.4    .045       0   358.4      .1       0
Bank Sta=343.4,358.4
XS Rating Curve= 0 ,0
Exp/Cntr=0.3,0.1

Type RM Length L Ch R = 1 ,8900.7  ,728.2,734.7,741.1
XS GIS Cut Line= 2
     1823520.582      610134.536     1822877.261      609727.096
#Sta/Elev= 30
       0  802.13     9.8   802.5    19.5  801.39    29.3  798.76   175.7  748.93
   234.3   726.1   244.1   723.9   253.8  723.14   273.1   722.8   283.1  722.79
   288.1  722.93   341.7  724.82   351.5  725.93   361.2  728.46   400.3  741.28
   429.6  750.08   478.4  768.33   488.1  772.33   507.7  781.78   517.4  785.29
   527.2  787.19   546.7  788.86   556.5  788.93     576  787.52   605.3  784.33
   624.8  783.21   644.3  785.18   712.7  797.08   732.2   799.3   761.5  801.11
#Mann= 3 , 0 , 0
       0      .1       0   273.1    .045       0   288.1      .1       0
Bank Sta=273.1,288.1
XS Rating Curve= 0 ,0
Exp/Cntr=0.3,0.1

Type RM Length L Ch R = 1 ,8165.7  ,490.7,484.2,477.8
XS GIS Cut Line= 2
     1824055.578      609785.894     1823652.442      609331.147
#Sta/Elev= 30
       0  794.96    19.6  792.32    39.2  788.43    58.8  782.24    68.6  778.44
    88.2  769.72   117.6  754.48   137.2  745.13   166.6  733.73   186.2  727.96
     196  726.66   205.8   726.1   274.4  723.62   284.2  722.63   302.5  719.52
   313.7  719.08   323.5  719.96   333.3  724.67   352.9  736.84   362.7  741.47
   431.3  765.29   441.1  768.36   450.9  770.63   470.5  773.57   519.5  777.35
   529.3  777.64   548.9  776.69   568.5  774.51   588.1   773.1   607.7  774.76
#Mann= 3 , 0 , 0
       0      .1       0   302.5    .045       0   323.5      .1       0
Bank Sta=302.5,323.5
XS Rating Curve= 0 ,0
Exp/Cntr=0.3,0.1

Type RM Length L Ch R = 1 ,7681.4  ,553.6,553.5,553.4
XS GIS Cut Line= 2
     1824458.495      609458.494     1823783.555      609028.668
#Sta/Elev= 30
       0  761.14    19.5   763.6    29.3  765.39    68.3  774.88    78.1  776.71
   146.4   782.5   156.1   782.8   165.9  781.58   175.6   778.6   185.4   774.1
   224.4  751.56   234.2  744.76   253.7  727.74   263.5  722.24   275.3  719.79
     283     719   292.8  718.95     322  722.03   390.3   723.2   536.7  723.64
   556.2  724.54     566   725.7   595.3  730.69   663.6  743.44   702.6  751.63
   722.1  756.37   741.6     763   761.2   771.5   780.7  781.19   800.2  791.61
#Mann= 3 , 0 , 0
       0     .06       0   275.3    .045       0   292.8     .06       0
Bank Sta=275.3,292.8
XS Rating Curve= 0 ,0
Exp/Cntr=0.3,0.1

Type RM Length L Ch R = 1 ,7127.7  ,539,552,565
XS GIS Cut Line= 2
     1824572.316      608945.692     1824058.503      608621.178
#Sta/Elev= 30
       0  813.76    19.6  811.53    29.4  809.98    39.2  808.07      49   805.5
    58.8   802.3    78.4  794.84      98  786.48   137.2  768.54   166.6   756.1
   176.4  751.53   186.2  744.44     196  735.71   205.8  728.08   215.6  723.06
   225.4   719.9   235.2  718.23     245  717.94   284.2  718.23     294  718.08
   312.1  716.79   323.5  716.38   343.1  717.17   519.5  726.25   548.9  727.47
   558.7  729.95   568.5  734.16   578.3  738.84   588.1  743.92   607.7  755.03
#Mann= 3 , 0 , 0
       0     .06       0   312.1    .045       0   343.1     .06       0
Bank Sta=312.1,343.1
XS Rating Curve= 0 ,0
Exp/Cntr=0.3,0.1

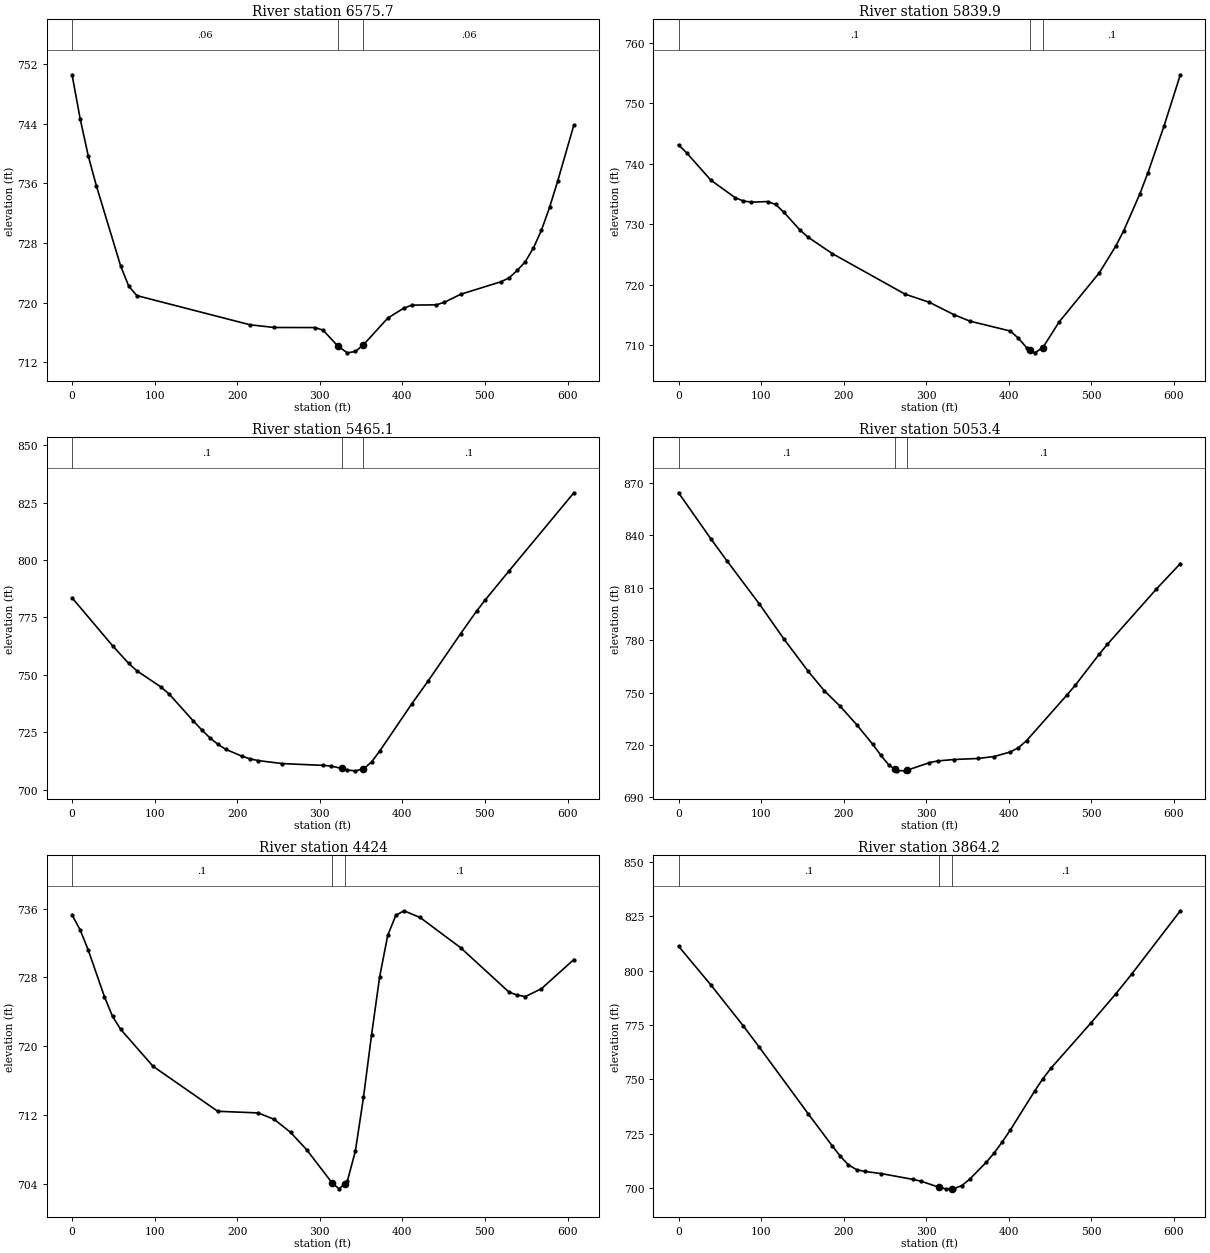
Type RM Length L Ch R = 1 ,6575.7  ,741.3,735.5,729.8
XS GIS Cut Line= 2
     1824648.769      608575.545     1824377.493      608031.741
#Sta/Elev= 30
       0  750.58     9.8  744.68    19.6   739.7    29.4   735.7    58.8  724.95
    68.6  722.23    78.4  720.96   215.6  717.04     245  716.68     294  716.67
   303.9  716.33   321.5  714.23   333.3  713.28   343.1  713.46   352.9  714.36
   382.3  717.94   401.9  719.29   411.7  719.68   441.1  719.72   450.9  720.06
   470.5  721.13   519.5  722.82   529.3  723.34   539.1  724.34   548.9  725.51
   558.7  727.34   568.5  729.75   578.3   732.8   588.1  736.31   607.7  743.84
#Mann= 3 , 0 , 0
       0     .06       0   321.5    .045       0   352.9     .06       0
Bank Sta=321.5,352.9
XS Rating Curve= 0 ,0
Exp/Cntr=0.3,0.1

Type RM Length L Ch R = 1 ,5839.9  ,382.4,374.7,367
XS GIS Cut Line= 2
      1825431.57      608472.535     1825050.105      607999.463
#Sta/Elev= 30
       0  743.12     9.8   741.8    39.2  737.27    68.6  734.38    78.4  733.84
    88.2  733.64   107.8  733.74   117.6  733.26   127.4     732     147  729.04
   156.8  727.86   186.2  725.14   274.4  718.43   303.9  717.08   333.3  715.05
   352.9  713.97   401.9  712.33   411.7  711.13   421.5   709.6   426.1  709.19
   431.3  708.73   441.1  709.57   460.7   713.8   509.7  721.98   529.3  726.32
   539.1  728.91   558.7  735.01   568.5  738.52   588.1  746.29   607.7   754.7
#Mann= 3 , 0 , 0
       0      .1       0   426.1    .045       0   441.1      .1       0
Bank Sta=426.1,441.1
XS Rating Curve= 0 ,0
Exp/Cntr=0.3,0.1

Type RM Length L Ch R = 1 ,5465.1  ,418.7,411.5,404.3
XS GIS Cut Line= 2
     1825711.341       608060.06     1825197.528      607735.546
#Sta/Elev= 30
       0  783.57      49  762.71    68.6  755.01    78.4  751.81   107.8  744.71
   117.6  741.66     147   729.9   156.8  726.18   166.6  722.72   176.4  719.85
   186.2  717.61   205.8  714.62   215.6  713.48   225.4  712.72   254.8  711.41
   303.9  710.64   313.7  710.35   326.5  709.29   333.3   708.6   343.1  708.26
   352.9  709.05   362.7  712.12   372.5  716.84   411.7  737.56   431.3  747.42
   470.5  767.92   490.1  777.87   499.9  782.44   529.3   795.3   607.7  829.27
#Mann= 3 , 0 , 0
       0      .1       0   326.5    .045       0   352.9      .1       0
Bank Sta=326.5,352.9
XS Rating Curve= 0 ,0
Exp/Cntr=0.3,0.1

Type RM Length L Ch R = 1 ,5053.4  ,624.4,629.4,634.4
XS GIS Cut Line= 2
     1826015.873      607712.191     1825425.423      607568.379
#Sta/Elev= 30
       0  864.46    39.2  838.05    58.8  825.37      98  800.66   127.4  780.83
   156.8  762.32   176.4  751.13     196  742.04   215.6  731.66   235.2  720.35
     245  714.08   254.8  708.41   261.8  706.22   264.6  705.34   274.4  705.15
   276.8  705.49   303.9  709.85   313.7  710.81   333.3  711.64   362.7  712.23
   382.3  713.36   401.9  715.98   411.7  718.44   421.5  722.46   470.5  748.66
   480.3  754.08   509.7  772.11   519.5   777.7   578.3   809.1   607.7  823.91
#Mann= 3 , 0 , 0
       0      .1       0   261.8    .045       0   276.8      .1       0
Bank Sta=261.8,276.8
XS Rating Curve= 0 ,0
Exp/Cntr=0.3,0.1

Type RM Length L Ch R = 1 ,4424    ,538.5,559.5,580.5
XS GIS Cut Line= 2
      1826104.82      607181.237     1825559.976      606912.056
#Sta/Elev= 30
       0  735.27     9.8  733.52    19.6  731.18    39.2  725.76      49  723.46
    58.8  721.97      98  717.67   176.4  712.43   225.4  712.24     245  711.48
   264.6  709.98   284.2  707.95   315.3  704.05   323.5  703.41   330.3  704.01
   333.3  704.27   343.1   707.8   352.9  714.04   362.7  721.32   372.5  728.07
   382.3   732.9   392.1  735.22   401.9  735.75   421.5  734.97   470.5  731.46
   529.3  726.28   539.1  725.95   548.9  725.77   568.5  726.69   607.7  730.08
#Mann= 3 , 0 , 0
       0      .1       0   315.3    .045       0   330.3      .1       0
Bank Sta=315.3,330.3
XS Rating Curve= 0 ,0
Exp/Cntr=0.3,0.1

Type RM Length L Ch R = 1 ,3864.2  ,477.5,456.8,439.1
XS GIS Cut Line= 2
     1826320.793      607074.256     1826210.184      606476.695
#Sta/Elev= 30
       0  811.26    39.2  793.42    78.4  774.62      98  764.71   156.8  734.29
   186.2  719.39     196  714.61   205.8  710.65   215.6  708.48   225.4  707.66
     245   706.7   284.2  703.98     294  703.12   315.9  700.32   323.5  699.65
   330.9   699.7   333.3  699.71   343.1  701.13   352.9  704.21   372.5  711.78
   382.3  716.16   392.1  721.26   401.9  726.76   431.3  744.62   441.1  750.23
   450.9  755.08   499.9  776.15   529.3  789.23   548.9  798.45   607.7  827.55
#Mann= 3 , 0 , 0
       0      .1       0   315.9    .045       0   330.9      .1       0
Bank Sta=315.9,330.9
XS Rating Curve= 0 ,0
Exp/Cntr=0.3,0.1

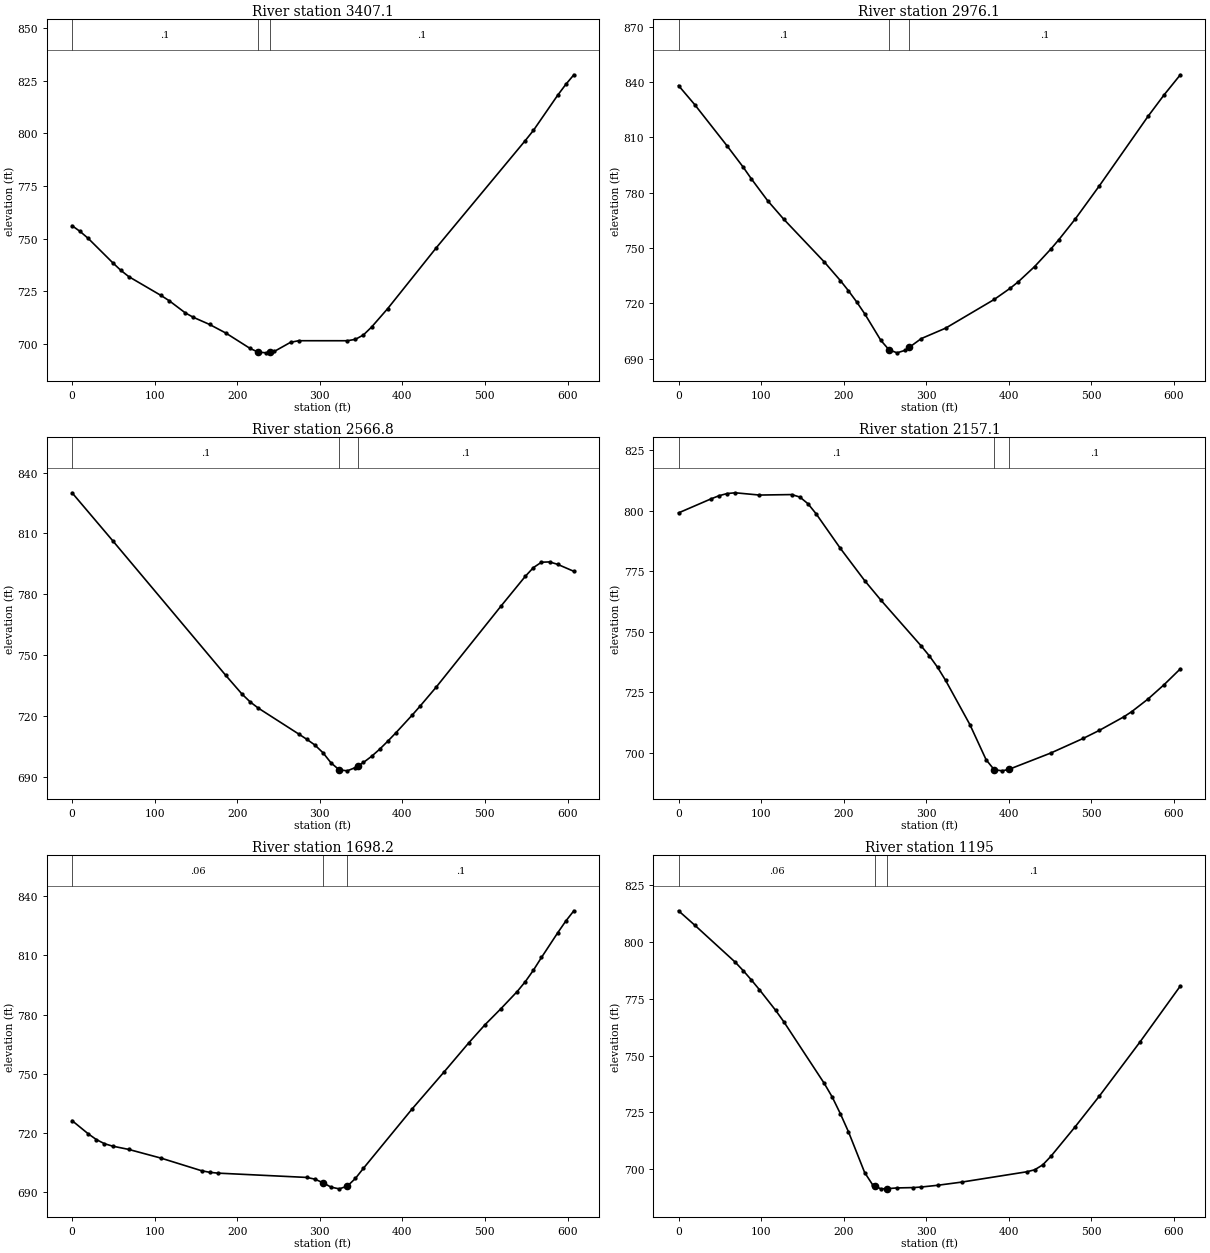
Type RM Length L Ch R = 1 ,3407.1  ,430.7,430.5,430.4
XS GIS Cut Line= 2
       1826853.3      606768.982     1826339.487      606444.468
#Sta/Elev= 30
       0  756.16     9.8  753.41    19.6  750.12      49  738.68    58.8  735.07
    68.6  732.02   107.8  723.05   117.6  720.58   137.2  714.78     147  712.68
   166.6   709.3   186.2  705.24   215.6  697.94   225.2  696.21   235.2  695.85
   240.2   696.2     245  696.54   264.6  700.84   274.4   701.6   333.3  701.59
   343.1  702.25   352.9  704.35   362.7  708.07   382.3  716.86   441.1   745.7
   548.9  796.56   558.7  801.35   588.1  818.04   597.9  823.17   607.7  827.75
#Mann= 3 , 0 , 0
       0      .1       0   225.2    .045       0   240.2      .1       0
Bank Sta=225.2,240.2
XS Rating Curve= 0 ,0
Exp/Cntr=0.3,0.1

Type RM Length L Ch R = 1 ,2976.1  ,409.7,409.6,409.5
XS GIS Cut Line= 2
     1827053.863      606417.752      1826540.05      606093.238
#Sta/Elev= 30
       0  838.18    19.6  827.84    58.8  805.46    78.4  793.86    88.2  787.55
   107.8  775.77   127.4  765.66   176.4  742.51     196  732.34   205.8   726.8
   215.6  720.85   225.4  714.37     245  699.89   254.8  694.83   264.6  693.12
   274.4  694.48   279.7  696.19     294  700.86   323.5  706.53   382.3  722.09
   401.9  728.25   411.7  731.79   431.3  739.98   450.9  749.46   460.7  754.61
   480.3  765.67   509.7  783.81   568.5  821.44   588.1  833.17   607.7  844.04
#Mann= 3 , 0 , 0
       0      .1       0   254.8    .045       0   279.7      .1       0
Bank Sta=254.8,279.7
XS Rating Curve= 0 ,0
Exp/Cntr=0.3,0.1

Type RM Length L Ch R = 1 ,2566.8  ,409.8,409.6,409.4
XS GIS Cut Line= 2
      1827267.46      606079.556     1826753.647      605755.043
#Sta/Elev= 30
       0  830.06      49  806.51   186.2  739.93   205.8  730.74   215.6   726.9
   225.4  723.85   274.4  711.05   284.2  708.44     294  705.62   303.9  701.78
   313.7  696.75   323.5  693.36   333.3  692.86   343.1  694.48   346.2  695.28
   352.9  697.01   362.7  700.01   372.5  703.53   382.3  707.47   392.1   711.6
   411.7  720.27   421.5   724.8   441.1  734.22   519.5  774.17   548.9  788.84
   558.7  793.14   568.5   795.8   578.3  795.95   588.1  794.74   607.7   791.3
#Mann= 3 , 0 , 0
       0      .1       0   323.5    .045       0   346.2      .1       0
Bank Sta=323.5,346.2
XS Rating Curve= 0 ,0
Exp/Cntr=0.3,0.1

Type RM Length L Ch R = 1 ,2157.1  ,454.1,458.7,462.2
XS GIS Cut Line= 2
     1827481.057      605741.361     1826967.244      605416.847
#Sta/Elev= 30
       0  799.04    39.2  804.81      49  806.13    58.8  807.03    68.6  807.35
      98  806.41   137.2  806.61     147  805.57   156.8  802.81   166.6  798.68
     196  784.38   225.4  771.07     245  763.03     294  744.02   303.9  739.91
   313.7  735.25   323.5  729.81   352.9  711.55   372.5  697.06   382.3  692.94
   392.1  692.48   400.4  693.13   450.9  699.85   490.1  705.88   509.7  709.21
   539.1  714.76   548.9  716.95   568.5  722.13   588.1  728.09   607.7  734.61
#Mann= 3 , 0 , 0
       0      .1       0   382.3    .045       0   400.4      .1       0
Bank Sta=382.3,400.4
XS Rating Curve= 0 ,0
Exp/Cntr=0.3,0.1

Type RM Length L Ch R = 1 ,1698.2  ,511.6,503.1,495.6
XS GIS Cut Line= 2
     1827606.254      605393.685     1827171.683      604968.877
#Sta/Elev= 30
       0  726.26    19.6  719.56    29.4  716.66    39.2  714.57      49  713.33
    68.6  711.66   107.8  707.24   156.8  700.86   166.6  700.06   176.4  699.65
   284.2  697.46     294   696.6   303.9  694.76   313.7  692.53   323.5  691.68
   333.3  693.03   343.1  696.94   352.9  702.11   411.7  732.12   450.9  751.11
   480.3  765.62   499.9  774.78   519.5  783.05   539.1   791.7   548.9  796.69
   558.7   802.5   568.5  808.97   588.1  821.44   597.9  827.39   607.7  832.62
#Mann= 3 , 0 , 0
       0     .06       0   303.9    .045       0   333.3      .1       0
Bank Sta=303.9,333.3
XS Rating Curve= 0 ,0
Exp/Cntr=0.3,0.1

Type RM Length L Ch R = 1 ,1195    ,264.7,270,275.3
XS GIS Cut Line= 2
      1827953.22      604971.132     1827384.246      604757.633
#Sta/Elev= 30
       0  813.61    19.6   807.3    68.6  791.05    78.4  787.28    88.2  783.21
      98  778.92   117.6  769.86   127.4  764.89   176.4   737.8   186.2  731.71
     196  724.41   205.8  716.48   225.4  698.58   235.2   693.1   237.7  692.67
     245  691.41   252.7  691.49   264.6  691.81   284.2  691.96     294  692.21
   313.7  692.97   343.1  694.38   421.5  698.89   431.3  699.78   441.1  701.95
   450.9  705.68   480.3  718.67   509.7   732.2   558.7  755.88   607.7  780.55
#Mann= 3 , 0 , 0
       0     .06       0   237.7    .045       0   252.7      .1       0
Bank Sta=237.7,252.7
XS Rating Curve= 0 ,0
Exp/Cntr=0.3,0.1

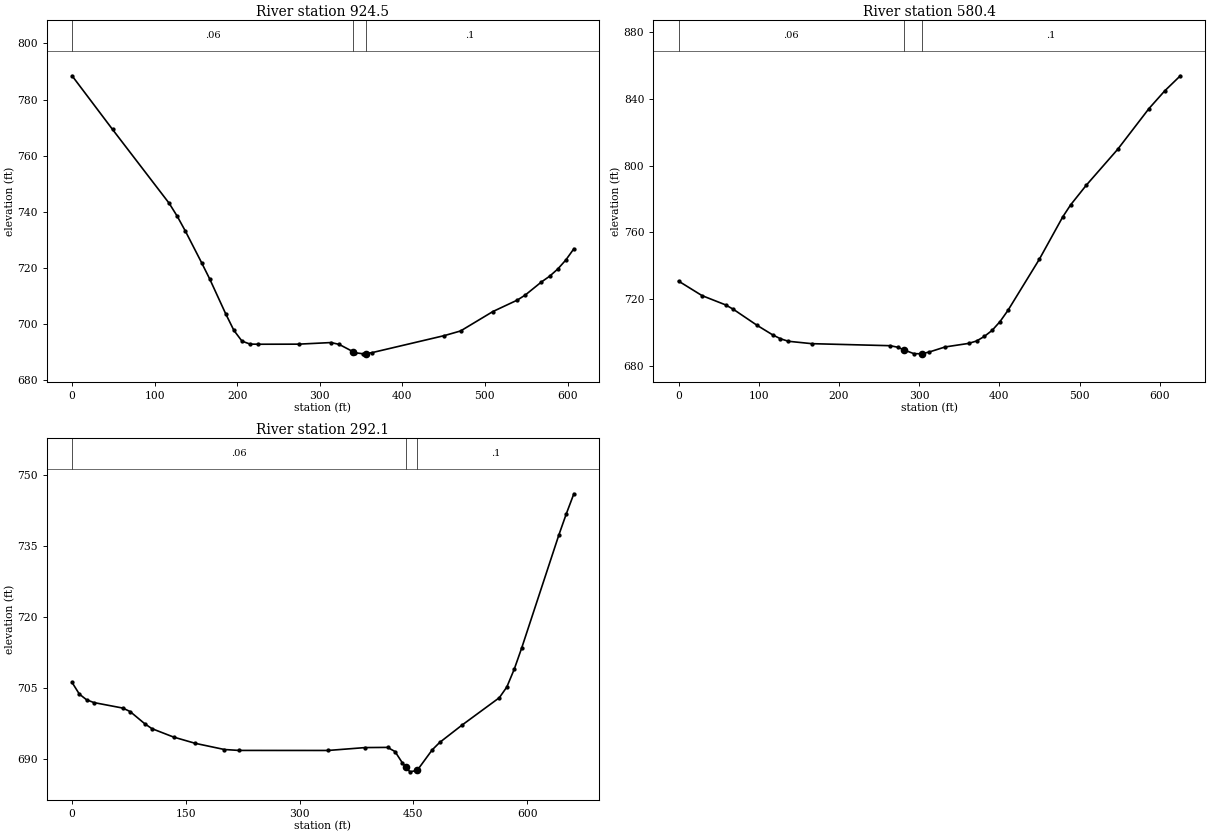
Type RM Length L Ch R = 1 ,924.5   ,336.5,344,351.5
XS GIS Cut Line= 2
     1828016.216      604817.576     1827519.697      604467.173
#Sta/Elev= 30
       0  788.48      49  769.37   117.6  743.05   127.4  738.42   137.2  733.16
   156.8  721.93   166.6  716.15   186.2  703.59     196  697.77   205.8  693.94
   215.6  692.89   225.4  692.84   274.4  692.87   313.7  693.44   323.5  692.78
   340.6  690.14   343.1   689.8   352.9  689.42   355.6  689.53   362.7  689.81
   450.9  695.92   470.5  697.57   509.7   704.5   539.1  708.55   548.9  710.38
   568.5  715.04   578.3  717.06   588.1   719.6   597.9  722.83   607.7  726.84
#Mann= 3 , 0 , 0
       0     .06       0   340.6    .045       0   355.6      .1       0
Bank Sta=340.6,355.6
XS Rating Curve= 0 ,0
Exp/Cntr=0.3,0.1

Type RM Length L Ch R = 1 ,580.4   ,290.5,288.3,286.1
XS GIS Cut Line= 2
     1828187.781      604664.654     1827818.196      604159.855
#Sta/Elev= 30
       0  730.94    29.3  722.25    58.6  716.72    68.4  714.05    97.8  704.52
   117.3  698.79   127.1  696.45   136.9  694.95   166.2  693.51   263.9   692.3
   273.7  691.34   280.7  689.82   293.3  687.57     303  687.43   312.8  688.56
   332.4  691.55   361.7  693.67   371.5   695.1   381.2  697.82     391  701.48
   400.8  706.71   410.6  713.35   449.7  743.89     479  769.32   488.8  776.49
   508.3  788.24   547.4  809.68   586.5   834.1   606.1  844.66   625.6  853.71
#Mann= 3 , 0 , 0
       0     .06       0   280.7    .045       0     303      .1       0
Bank Sta=280.7,303
XS Rating Curve= 0 ,0
Exp/Cntr=0.3,0.1

Type RM Length L Ch R = 1 ,292.1   ,282.6,291.9,301.1
XS GIS Cut Line= 3
     1828300.863       604595.48     1828318.402      604356.955
     1828037.783      604041.259
#Sta/Elev= 30
       0  706.21     9.6  703.75    19.1  702.55    28.7  701.96      67  700.79
    76.5  700.06    95.7   697.5   105.2  696.45   133.9  694.66   162.6  693.33
   200.9  692.03     220  691.84   337.4  691.83   386.5  692.44     416  692.48
   425.8   691.6   435.6  689.18   440.1  688.32   445.4  687.31   455.1  687.63
   474.9  691.97   484.7  693.53   514.2   697.2   563.3  702.98   573.2  705.24
     583  709.02   592.8  713.49   641.9  737.44   651.7   741.9   661.6  746.11
#Mann= 3 , 0 , 0
       0     .06       0   440.1    .045       0   455.1      .1       0
Bank Sta=440.1,455.1
XS Rating Curve= 0 ,0
Exp/Cntr=0.3,0.1

Chan Stop Cuts=-1
Use User Specified Reach Order=0
Composite Channel Slope=5